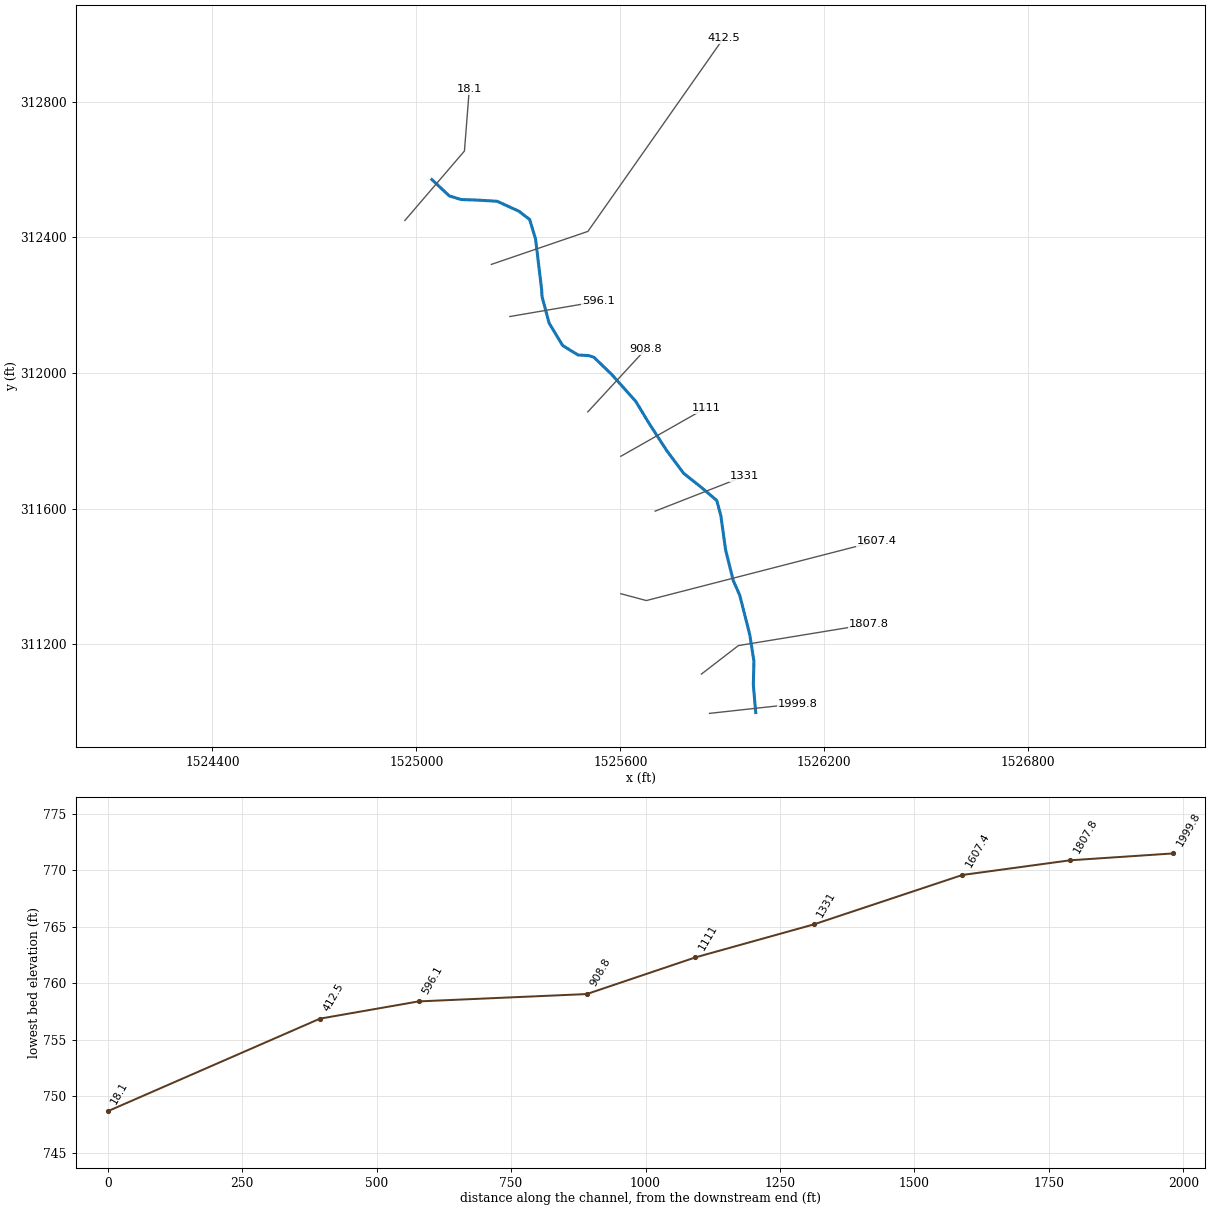
--- SFRockRn.prj (project) ---

Proj Title=SFRockRn
Current Plan=p01
Default Exp/Contr=0,0
English Units
Geom File=g01
Flow File=f01
Plan File=p01
BEGIN DESCRIPTION:
AMEC Environment & Infrastructure, 2013
Projection: NAD 1983 State Plane West Virginia North FIPS 4701 (US Feet)
Vertical Datum: NAVD 1988
END DESCRIPTION:
DSS Export Rating Curves= 0
DSS Export Rating Curve Sorted= 0
DSS Export Volume Flow Curves= 0
DXF OffsetX= 0
DXF OffsetY= 0
DXF ScaleX= 0
DXF ScaleY= 0

--- SFRockRn.p01 (plan) ---

Plan Title=Floodplain
Program Version=4.00
Geom File=g01
Flow File=f01
K Sum by GR=0
Std Step Tol=0.01
Critical Tol=0.01
Num of Std Step Trials=20
Max Error Tol=0.3
Flow Tol Ratio=0.001
Split Flow NTrial=30
Split Flow Tol=0.02
Split Flow Ratio=0.02
Log Output Level=0
Friction Slope Method=1
Unsteady Friction Slope Method=2
Unsteady Bridges Friction Slope Method=1
Global Log Level=0
CheckData=False
Run HTab=0
Run UNet=0
Run PostProcess=0
UNET Theta=0
UNET Theta Warmup=0
UNET ZTol=0
UNET ZSATol=0
UNET MxIter=0
UNET MaxInSteps=0
UNET DtIC=0
UNET DtMin=0
UNET MaxCRTS=0
UNET WFStab=0
UNET SFStab=0
UNET WFX=0
UNET SFX=0
UNET DSS MLevel=0
UNET DZMax Abort=0
UNET Convert EG Bridges=0
UNET Use Existing IB Tables=0
UNET Froude Limit=0
UNET Froude Power=0
Write IC File=0
Echo Input=False
Echo Output=False
Write Detailed=0

--- SFRockRn.f01 (steady flow) ---

Flow Title=USGS Regress. Eqn. (2010) - Western-Plateaus
Program Version=4.10
Number of Profiles= 1
Profile Names=P100yr
River Rch & RM=SFRockRn,Main            ,1999.8
     815
River Rch & RM=SFRockRn,Main            ,1331
     842
River Rch & RM=SFRockRn,Main            ,1111
     925
River Rch & RM=SFRockRn,Main            ,596.1
     938
River Rch & RM=SFRockRn,Main            ,18.1
     941
Boundary for River Rch & Prof#=SFRockRn,Main            , 1
Up Type= 0
Dn Type= 1
Dn Known WS=755
DSS Import GetInterval= 0
DSS Import GetPeak= 0
DSS Import FillOption= 0

--- SFRockRn.g01 (geometry) ---

Geom Title=USGS 3m DEM
Program Version=4.10

River Reach=SFRockRn        ,Main
Reach XY= 30
     1525998.289      310999.193     1525991.244      311081.093
      1525992.98      311150.537     1525980.827      311228.662
     1525951.313      311344.982     1525932.216      311388.385
     1525909.646      311478.662     1525895.758      311579.357
     1525883.605      311624.496      1525836.73      311664.426
     1525786.383      311704.357     1525736.035      311772.065
     1525682.216      311855.399     1525645.758      311916.162
     1525574.577      311996.024     1525522.494      312046.371
     1525506.869      312051.579     1525475.619      312053.315
      1525430.48      312081.093     1525390.549      312147.065
     1525369.716       312225.19      1525368.39      312247.066
     1525350.619      312395.329     1525333.258      312452.621
     1525302.008      312476.926     1525237.771       312506.44
      1525180.48      312509.912     1525131.869      312511.649
     1525097.146      312522.065     1525045.589        312570.4

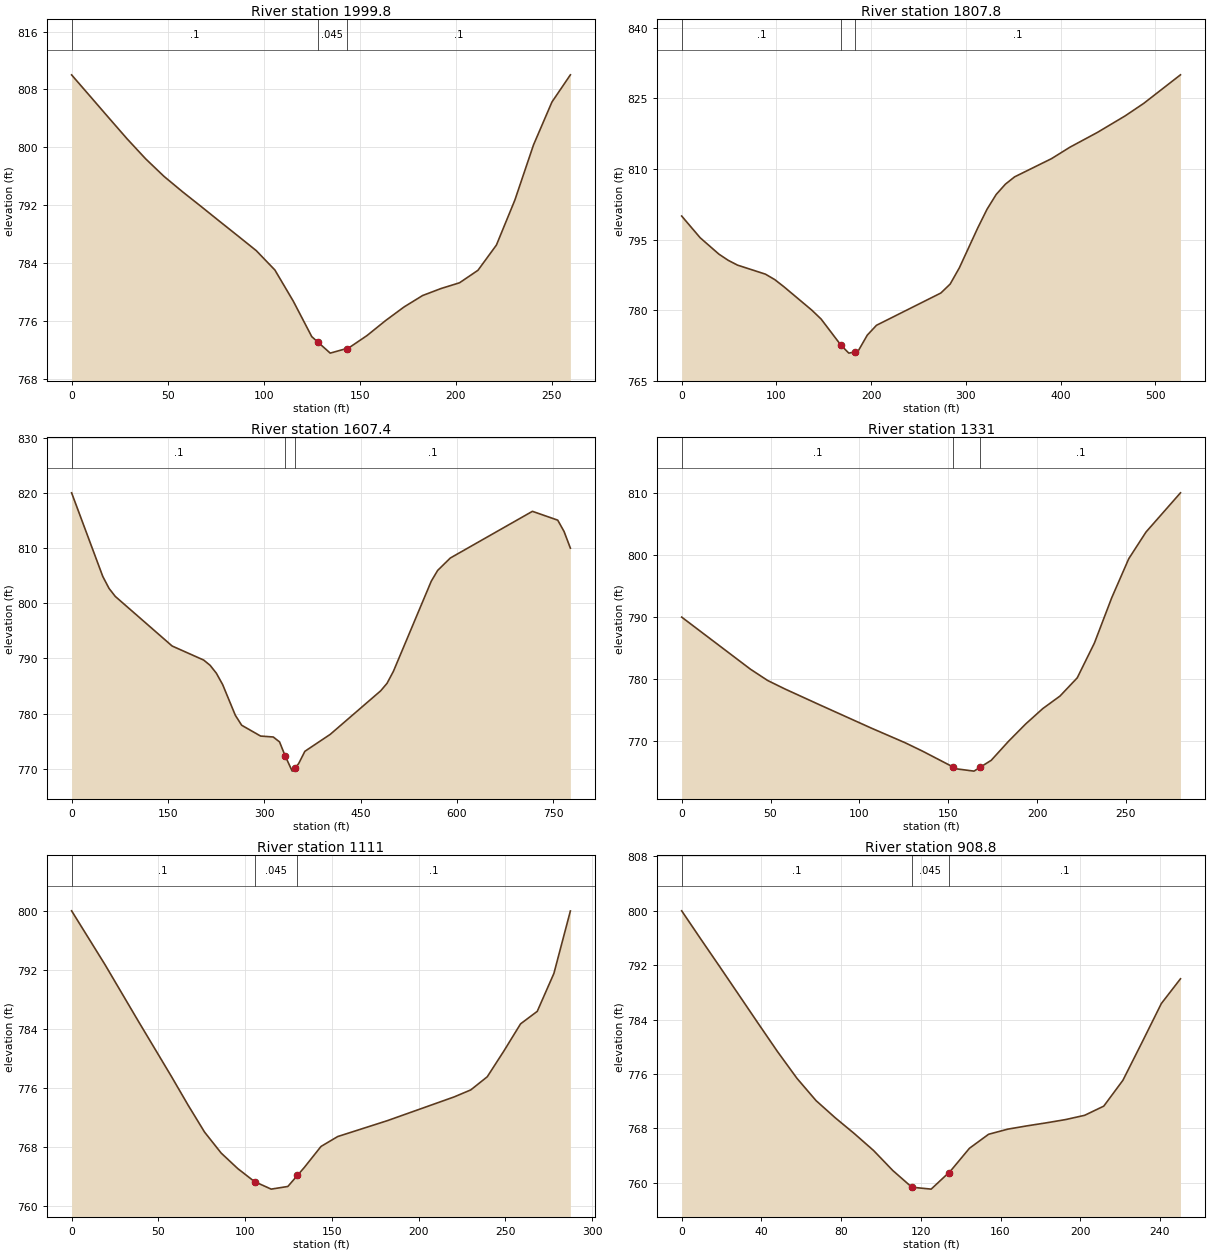
Type RM Length L Ch R = 1 ,1999.8  ,190.8,192,193.2
XS GIS Cut Line= 2
     1525862.353       310996.87     1526120.377       311025.29
#Sta/Elev= 30
       0     810     9.6  807.06    19.2  804.11    28.8  801.18    38.5   798.4
    48.1  795.96    57.7  793.84    67.3  791.82    76.9  789.77    86.5  787.74
    96.1  785.69   105.8  783.01   115.4  778.69     125  773.79   128.2  773.03
   134.6  771.51   143.2  772.15   144.2  772.22   153.8  773.95   163.4  776.01
   173.1  777.91   182.7  779.48   192.3  780.45   201.9  781.24   211.5  782.97
   221.1  786.46   230.7  792.68   240.4  800.31     250  806.25   259.6  810.01
#Mann= 3 , 0 , 0
       0      .1       0   128.2    .045       0   143.2      .1       0
Bank Sta=128.2,143.2
XS Rating Curve= 0 ,0
Exp/Cntr=0.3,0.1

Type RM Length L Ch R = 1 ,1807.8  ,198.4,200.4,202.4
XS GIS Cut Line= 3
     1525838.435      311112.595      1525947.26      311196.661
     1526331.071      311259.722
#Sta/Elev= 30
       0  800.01    19.6  795.38    39.3  791.92    49.1  790.61    58.9  789.59
    88.4  787.67    98.2  786.52     108  784.98   137.5     780   147.2  778.13
   168.1  772.59   176.4   770.9   183.1  771.16   186.1  771.28   195.9  774.72
   205.6  776.81   273.6  783.67   283.4  785.57   293.1  789.02   312.5  797.48
   322.3  801.45     332   804.6   341.7  806.78   351.4  808.33   390.3  812.19
   409.8  814.63     439  817.79   468.1  821.28   487.6  823.92   526.5     830
#Mann= 3 , 0 , 0
       0      .1       0   168.1    .045       0   183.1      .1       0
Bank Sta=168.1,183.1
XS Rating Curve= 0 ,0
Exp/Cntr=0.3,0.1

Type RM Length L Ch R = 1 ,1607.4  ,274.7,276.4,278.9
XS GIS Cut Line= 3
     1525601.416      311349.614     1525676.519      311329.463
     1526353.152      311504.128
#Sta/Elev= 30
       0     820    48.6  804.84    58.3  802.69      68  801.24   156.5  792.26
   205.7  789.71   215.6  788.77   225.4  787.33   235.2  785.27   254.9  779.72
   264.8  777.91   294.3  775.95     314  775.78   323.8  774.89   332.6  772.33
   343.5   769.6   347.6  770.15   353.4  770.94   363.2  773.19   402.6  776.25
   481.3  784.15   491.1   785.5     501  787.66     560     804   569.9  805.94
   589.6  808.19   717.5  816.65   756.9  815.05   766.7  813.01   776.6  809.98
#Mann= 3 , 0 , 0
       0      .1       0   332.6    .045       0   347.6      .1       0
Bank Sta=332.6,347.6
XS Rating Curve= 0 ,0
Exp/Cntr=0.3,0.1

Type RM Length L Ch R = 1 ,1331    ,215.2,220,223.8
XS GIS Cut Line= 2
     1525702.413      311593.105     1525963.762      311695.446
#Sta/Elev= 23
       0     790    38.7  781.62    48.4   779.8    58.1  778.44    77.4  775.92
   106.5  772.17   125.8  769.78   135.5  768.44   152.9  765.86   154.8  765.58
   164.5  765.22   167.9  765.83   174.2  766.96   183.9  770.01   193.6  772.81
   203.2  775.28   212.9   777.3   222.6  780.23   232.3  785.85     242  793.11
   251.6   799.4   261.3  803.69   280.7     810
#Mann= 3 , 0 , 0
       0      .1       0   152.9    .045       0   167.9      .1       0
Bank Sta=152.9,167.9
XS Rating Curve= 0 ,0
Exp/Cntr=0.3,0.1

Type RM Length L Ch R = 1 ,1111    ,195.3,202.2,209.2
XS GIS Cut Line= 2
     1525601.541      311754.742     1525851.353       311896.92
#Sta/Elev= 24
       0     800    19.2  792.73    38.3  785.11    57.5  777.57    67.1  773.69
    76.6  770.03    86.2  767.18    95.8  765.07   105.4  763.32     115   762.3
   124.6  762.66   130.1  764.15   134.1  765.24   143.7  768.08   153.3  769.42
     182  771.58   220.4  774.79     230  775.74   239.5  777.52   249.1  781.02
   258.7  784.69   268.3  786.38   277.9  791.52   287.4  799.98
#Mann= 3 , 0 , 0
       0      .1       0   105.4    .045       0   130.1      .1       0
Bank Sta=105.4,130.1
XS Rating Curve= 0 ,0
Exp/Cntr=0.3,0.1

Type RM Length L Ch R = 1 ,908.8   ,327.7,312.6,297.6
XS GIS Cut Line= 2
     1525504.309      311885.598     1525673.926      312069.702
#Sta/Elev= 29
       0     800     9.6  795.84    19.3  791.69    28.9  787.54    38.5  783.39
    48.1  779.28    57.8  775.37    67.4  772.08      77  769.56    86.6  767.23
    96.3  764.73   105.9   761.8   115.5  759.33     119  759.23   125.2  759.05
     134  761.46   134.8  761.68   144.4  765.06     154  767.12   163.7  767.88
   173.3  768.36   182.9   768.8   192.6  769.28   202.2  769.91   211.8  771.26
   221.4  775.06   231.1   780.7   240.7  786.36   250.3     790
#Mann= 3 , 0 , 0
       0      .1       0   115.5    .045       0     134      .1       0
Bank Sta=115.5,134
XS Rating Curve= 0 ,0
Exp/Cntr=0.3,0.1

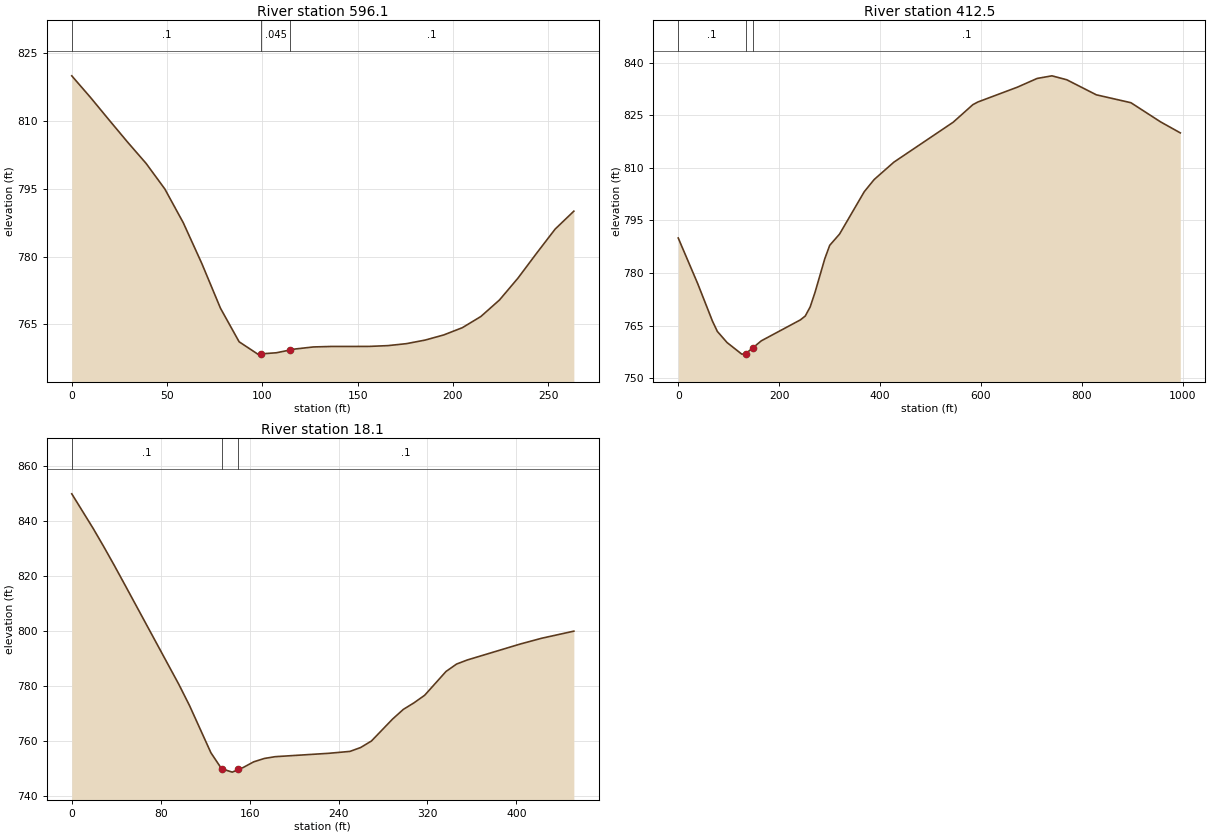
Type RM Length L Ch R = 1 ,596.1   ,179.8,183.6,187.2
XS GIS Cut Line= 2
     1525275.029      312166.744     1525534.643      312211.207
#Sta/Elev= 30
       0     820     9.8  815.23    19.5  810.27    29.3  805.32      39  800.61
    48.8  794.97    58.5  787.48    68.3  778.39      78  768.57    87.8  761.13
    97.6   758.4    99.5  758.46   107.3   758.7   114.5  759.31   117.1  759.53
   126.8  759.99   136.6   760.1   146.3   760.1   156.1  760.11   165.8  760.28
   175.6  760.72   185.4  761.51   195.1  762.64   204.9  764.25   214.6  766.72
   224.4  770.39   234.1  775.23   243.9  780.75   253.6  786.08   263.4  790.04
#Mann= 3 , 0 , 0
       0      .1       0    99.5    .045       0   114.5      .1       0
Bank Sta=99.5,114.5
XS Rating Curve= 0 ,0
Exp/Cntr=0.3,0.1

Type RM Length L Ch R = 1 ,412.5   ,382.2,394.5,406.8
XS GIS Cut Line= 3
      1525220.57      312320.361     1525504.589      312417.657
     1525903.223      312986.781
#Sta/Elev= 30
       0     790    38.7  776.95    67.8   766.3    77.5  763.35    96.8  760.17
   125.9  756.87   133.7     757   148.7  758.76   164.6  760.66   242.1  766.64
   251.8  767.75   261.5  770.34   271.2  774.54   290.5   784.1   300.2   787.9
   319.8  791.14   368.7  803.21   388.3  806.68   427.4  811.64   544.9  823.03
     584  828.05   593.8   828.8   672.1  833.03   711.3  835.52   740.6  836.27
     770  835.15   828.7  830.85   897.2   828.6   955.9  823.14   995.1  819.99
#Mann= 3 , 0 , 0
       0      .1       0   133.7    .045       0   148.7      .1       0
Bank Sta=133.7,148.7
XS Rating Curve= 0 ,0
Exp/Cntr=0.3,0.1

Type RM Length L Ch R = 1 ,18.1    ,19.1,18.1,17.1
XS GIS Cut Line= 3
     1524966.096      312449.744     1525141.376      312654.552
     1525155.609      312836.108
#Sta/Elev= 30
       0     850    19.3  837.37    28.9  830.68    38.5  823.76    48.1  816.64
    96.3  780.64   105.9  772.94   125.2  755.71   134.8   749.9     135  749.87
   144.4  748.67     150  749.63     154  750.31   163.7  752.42   173.3  753.65
   182.9  754.29   231.1  755.52   250.3  756.22   259.9  757.63   269.6     760
   288.7  768.02   298.3  771.51   307.9  773.91   317.5  776.66   336.7  785.32
   346.2  788.02   355.8   789.5   403.8  795.35   422.9  797.43   451.7     800
#Mann= 3 , 0 , 0
       0      .1       0     135    .045       0     150      .1       0
Bank Sta=135,150
XS Rating Curve= 0 ,0
Exp/Cntr=0.3,0.1

Chan Stop Cuts=-1
Use User Specified Reach Order=0
Composite Channel Slope=5